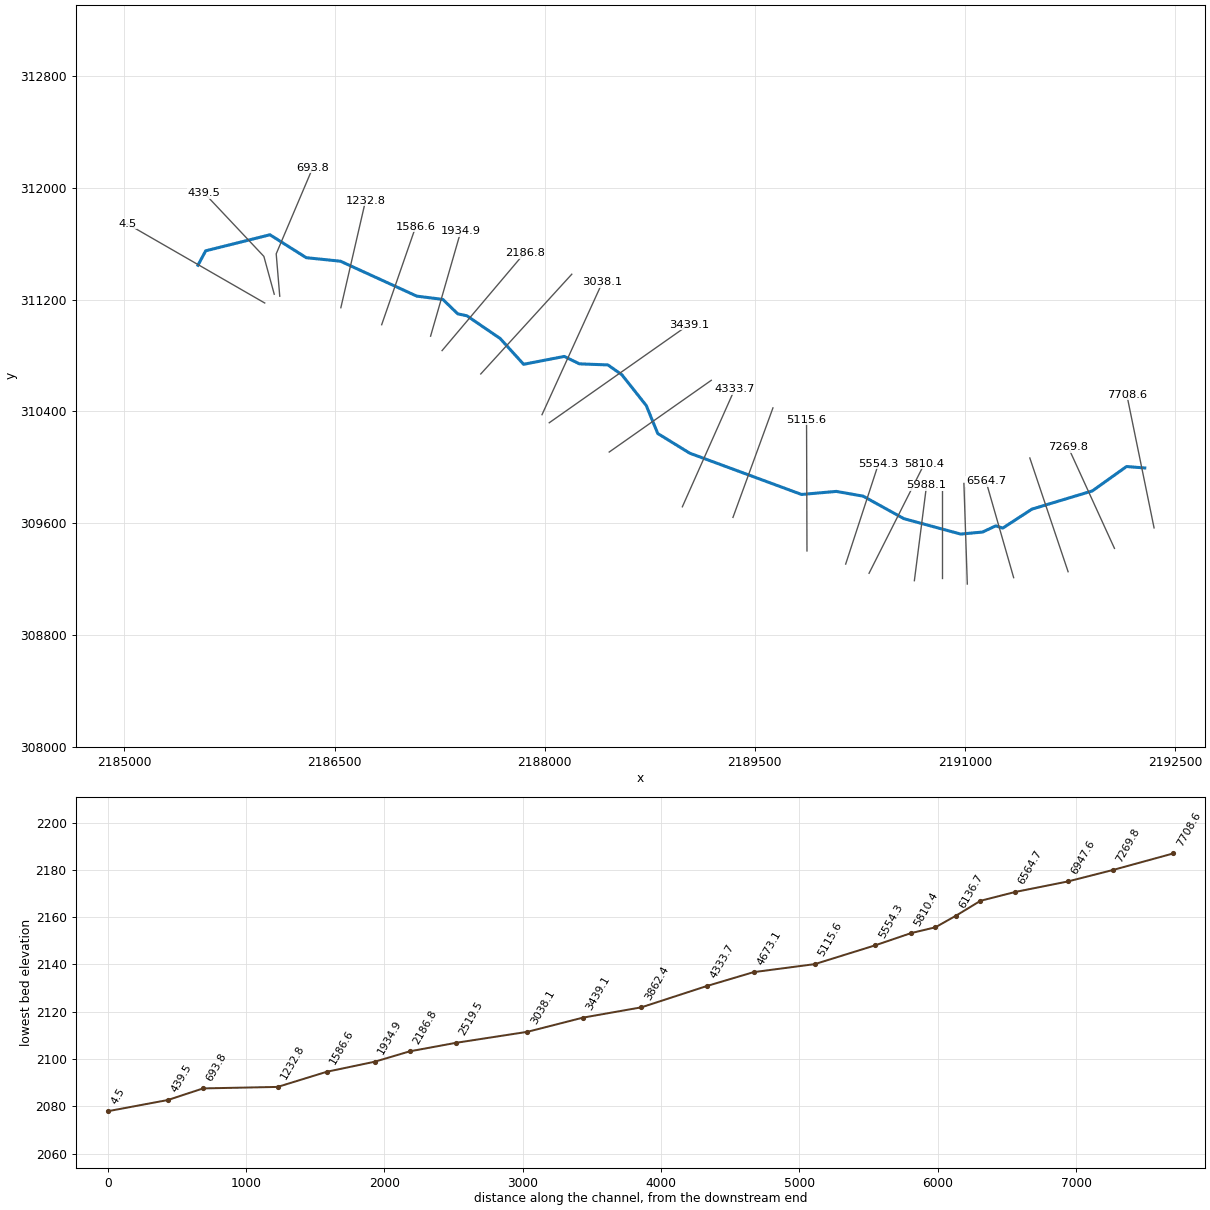
--- SlshLckRun.prj (project) ---

Proj Title=SlshLckRun
Current Plan=p01
Geom File=g01
Flow File=f01
Plan File=p01
DSS Export Rating Curves=0
DSS Export Rating Curve Sorted=0
DSS Export Volume Flow Curves=0
DXF OffsetX=0
DXF OffsetY=0
DXF ScaleX=0
DXF ScaleY=0

--- SlshLckRun.p01 (plan) ---

Plan Title=Floodplain
Program Version=4.00
Geom File=g01
Flow File=f01
K Sum by GR=0
Std Step Tol=0.01
Critical Tol=0.01
Num of Std Step Trials=20
Max Error Tol=0.3
Flow Tol Ratio=0.001
Split Flow NTrial=30
Split Flow Tol=0.02
Split Flow Ratio=0.02
Log Output Level=0
Friction Slope Method=1
Unsteady Friction Slope Method=2
Unsteady Bridges Friction Slope Method=1
Global Log Level=0
CheckData=False
Run HTab=0
Run UNet=0
Run PostProcess=0
UNET Theta=0
UNET Theta Warmup=0
UNET ZTol=0
UNET ZSATol=0
UNET MxIter=0
UNET MaxInSteps=0
UNET DtIC=0
UNET DtMin=0
UNET MaxCRTS=0
UNET WFStab=0
UNET SFStab=0
UNET WFX=0
UNET SFX=0
UNET DSS MLevel=0
UNET DZMax Abort=0
UNET Convert EG Bridges=0
UNET Use Existing IB Tables=0
UNET Froude Limit=0
UNET Froude Power=0
Write IC File=0
Echo Input=False
Echo Output=False
Write Detailed=0

--- SlshLckRun.f01 (steady flow) ---

Flow Title=NFF Regression Equation
Program Version=4.00
Number of Profiles=1
Profile Names=P100yr
River Rch & RM=SlshLckRun,Main      ,7708.6
651.5766
River Rch & RM=SlshLckRun,Main      ,6564.7
674.9006
River Rch & RM=SlshLckRun,Main      ,5115.6
741.8228
Boundary for River Rch & Prof#=SlshLckRun,Main      ,1
Up Type=0
Dn Type= 1
Dn Known WS=2081.5

--- SlshLckRun.g01 (geometry) ---

Geom Title=USGS 10m DEM
Program Version=4.10

River Reach=SlshLckRun      ,Main
Reach XY= 30
     2192284.659      309995.005     2192154.745      310005.544
     2191910.257      309830.859     2191479.016      309700.539
     2191271.068      309564.972     2191220.971       309581.22
     2191127.249      309536.794     2190970.352      309522.153
     2190564.903      309632.447      2190274.41      309793.228
      2190082.87      309827.419     2189834.433      309805.544
     2189035.995      310100.857      2188807.87      310241.482
     2188725.628      310441.791      2188551.62      310661.794
     2188451.911      310732.232     2188248.495       310739.92
     2188140.682      310793.044     2187850.058      310736.795
      2187682.87       310921.17      2187445.37       311083.67
     2187379.745      311097.732     2187273.495      311200.857
     2187087.557      311224.295     2186542.245      311474.294
     2186298.495      311499.294      2186039.12      311663.357
     2185580.289      311548.651     2185525.043      311445.105

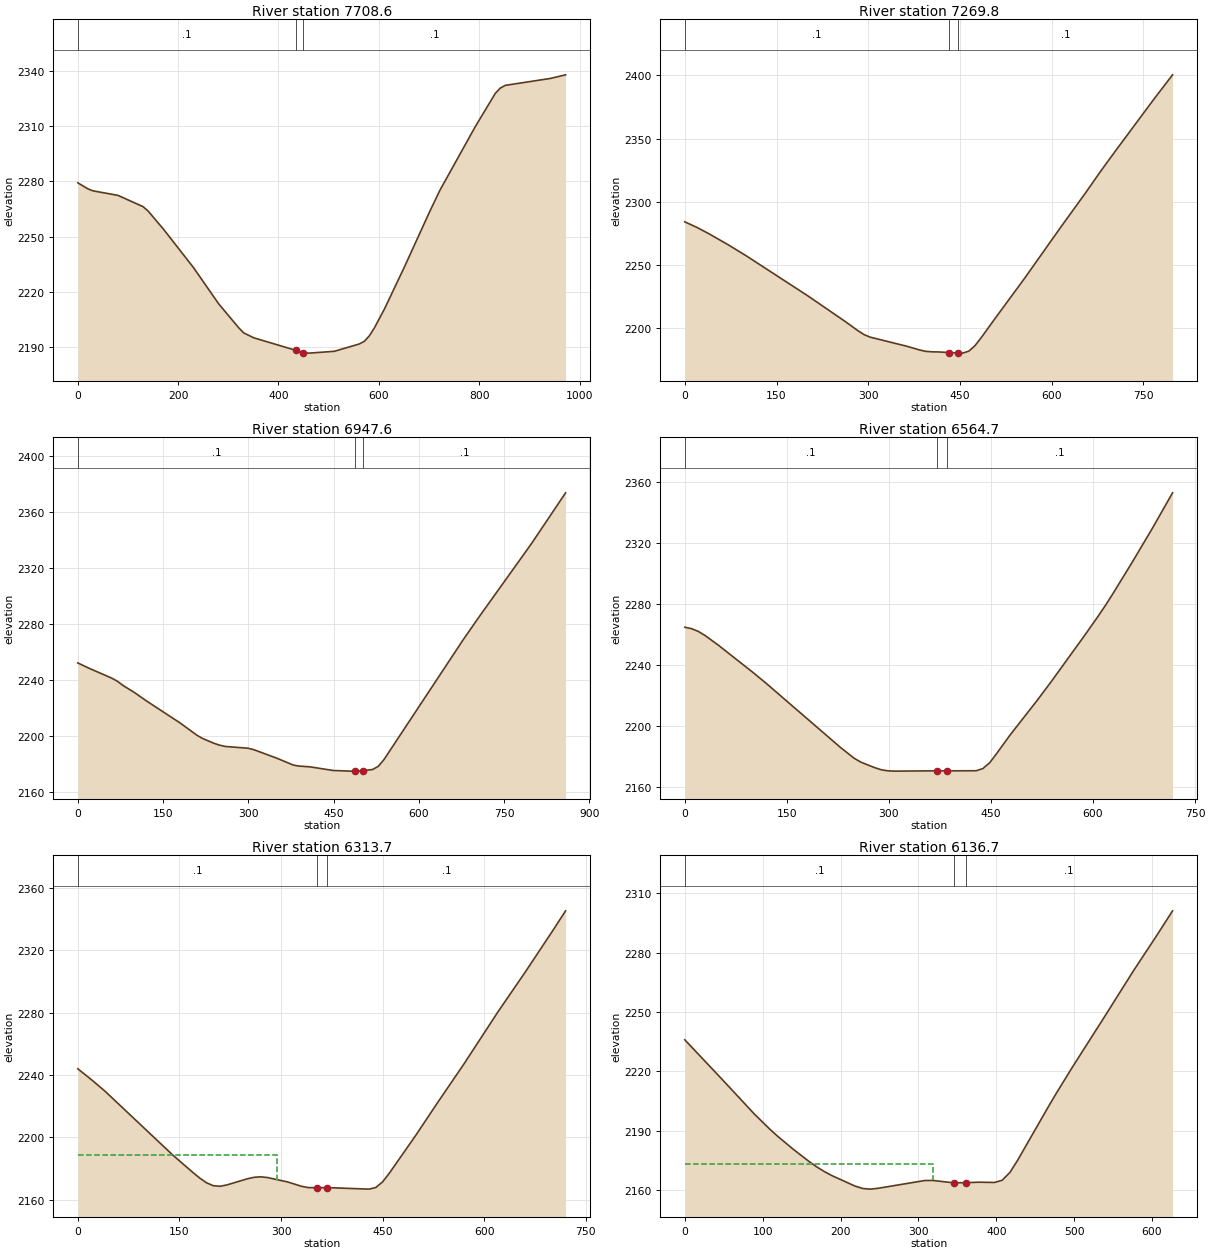
Type RM Length L Ch R = 1 ,7708.6  ,434.1,438.8,443.4
XS GIS Cut Line= 2
     2192351.027       309566.44     2192156.307      310518.944
#Sta/Elev= 30
       0 2279.26      20 2275.99    30.1 2274.91    80.2 2272.44   130.3  2266.3
   140.3  2263.9   170.4 2254.24   230.5 2233.34   280.6 2213.73   320.7 2200.69
   330.8 2197.87   350.8 2195.24   434.6 2188.45   449.6 2187.18     461 2186.94
   511.2 2187.92   561.3 2191.92   571.3 2193.38   581.3 2196.38   591.3 2200.69
   611.4 2210.99   651.5 2233.94   701.6  2263.8   721.6 2275.16   791.8 2309.51
   831.9 2327.64   841.9 2330.57   851.9 2332.07   942.1 2335.84   972.2 2337.79
#Mann= 3 , 0 , 0
       0      .1       0   434.6    .045       0   449.6      .1       0
Bank Sta=434.6,449.6
XS Rating Curve= 0 ,0
Exp/Cntr=0.3,0.1

Type RM Length L Ch R = 1 ,7269.8  ,324.3,322.2,319.7
XS GIS Cut Line= 2
     2192068.255      309419.815     2191737.302      310145.483
#Sta/Elev= 30
       0 2283.98    20.2 2279.49    40.4 2274.29    70.7 2265.88     101 2256.89
   201.9 2225.09   262.5 2204.92   282.7 2197.85   292.8 2194.67   302.9 2192.61
   363.4 2185.32   383.6 2182.47   393.7 2181.34   403.8 2180.95   413.9 2180.87
   432.5 2180.36   447.5 2179.98   454.3 2179.91   464.4 2181.46   474.5 2185.83
   484.6 2192.12   504.8 2205.69   555.3 2239.01   615.8 2280.45   656.2 2307.57
   676.4 2321.62   686.5 2328.45   706.7 2341.81   767.3 2381.39   797.6 2400.52
#Mann= 3 , 0 , 0
       0      .1       0   432.5    .045       0   447.5      .1       0
Bank Sta=432.5,447.5
XS Rating Curve= 0 ,0
Exp/Cntr=0.3,0.1

Type RM Length L Ch R = 1 ,6947.6  ,383,382.9,383.1
XS GIS Cut Line= 2
     2191737.302       309252.82     2191464.038       310066.54
#Sta/Elev= 30
       0  2252.3      20 2248.46    59.9 2241.42    69.9 2239.17    79.8 2236.15
    99.8 2231.15   119.8 2225.47   179.7 2209.56   209.6 2200.73   219.6  2198.4
   239.6 2194.97   249.5 2193.62   259.5 2192.72   299.4 2191.45   309.4 2190.46
   349.3 2184.48   379.3 2179.43   389.3 2178.72   409.2 2178.14   449.2 2175.57
   479.1 2175.11   487.7 2175.14   502.7 2175.43     519 2176.29     529  2178.6
     539 2183.47   678.7 2269.13   708.7 2286.59   798.5 2337.47   858.4 2373.64
#Mann= 3 , 0 , 0
       0      .1       0   487.7    .045       0   502.7      .1       0
Bank Sta=487.7,502.7
XS Rating Curve= 0 ,0
Exp/Cntr=0.3,0.1

Type RM Length L Ch R = 1 ,6564.7  ,257.3,251,244.7
XS GIS Cut Line= 2
      2191348.66      309210.313     2191151.302      309899.545
#Sta/Elev= 30
       0 2264.78      10 2263.82    19.9 2262.02    29.9 2259.34    49.8 2252.87
    99.6 2235.41   119.5 2228.11     229 2186.06   248.9 2179.06   258.9  2176.5
   278.8 2172.96   288.8 2171.53   298.7 2170.82   308.7 2170.64   370.3 2170.84
   385.3 2170.82   428.2 2170.89   438.1 2172.32   448.1 2176.14     458 2181.93
     478 2194.22   517.8 2216.86   537.7 2228.67   587.5 2259.32   607.4 2271.93
   617.4  2278.5   627.3 2285.34   657.2 2307.02   687.1  2329.4   716.9 2352.69
#Mann= 3 , 0 , 0
       0      .1       0   370.3    .045       0   385.3      .1       0
Bank Sta=370.3,385.3
XS Rating Curve= 0 ,0
Exp/Cntr=0.3,0.1

Type RM Length L Ch R = 1 ,6313.7  ,177.8,177,176.6
XS GIS Cut Line= 2
     2191017.707      309164.769     2190993.416      309884.364
#Sta/Elev= 30
       0 2243.98      20 2237.06      40  2229.7     140  2188.8     170 2177.53
     180 2173.98     190 2170.96     200 2169.09     210 2168.72     220 2169.59
     250 2173.49     260 2174.46     270 2174.79     280 2174.32     310 2171.47
     330 2168.73     340 2167.89   353.1 2167.83   368.1 2167.87     430  2166.9
     440 2167.96     450  2171.6     460 2177.19     500 2202.09     530 2221.62
     570 2247.08     620 2280.33     660 2305.65     700 2331.77     720 2345.17
#Mann= 3 , 0 , 0
       0      .1       0   353.1    .045       0   368.1      .1       0
#XS Ineff= 2 , 0
          294.28 2188.55
Permanent Ineff=
       F       F
Bank Sta=353.1,368.1
XS Rating Curve= 0 ,0
Exp/Cntr=0.3,0.1

Type RM Length L Ch R = 1 ,6136.7  ,151.3,148.6,145.4
XS GIS Cut Line= 2
     2190834.028      309206.956     2190834.028      309833.304
#Sta/Elev= 30
       0    2236    49.7 2215.29    89.5 2198.45   109.4  2190.8   119.3 2187.29
   139.2 2180.77   159.1 2174.72     169 2171.97     179 2169.54   188.9 2167.45
   218.7 2162.14   228.7 2160.92   238.6 2160.62   248.6 2161.06   308.2 2164.97
   318.2 2165.01   345.8 2163.78   360.8 2163.89   377.8 2164.12   397.7 2163.98
   407.6  2165.1   417.6  2169.1   427.5 2175.24   467.3 2202.51   477.2 2209.06
   497.1 2221.79   536.9 2246.32   576.6 2271.09   606.5 2288.91   626.4  2301.1
#Mann= 3 , 0 , 0
       0      .1       0   345.8    .045       0   360.8      .1       0
#XS Ineff= 2 , 0
          318.28 2173.17
Permanent Ineff=
       F       F
Bank Sta=345.8,360.8
XS Rating Curve= 0 ,0
Exp/Cntr=0.3,0.1

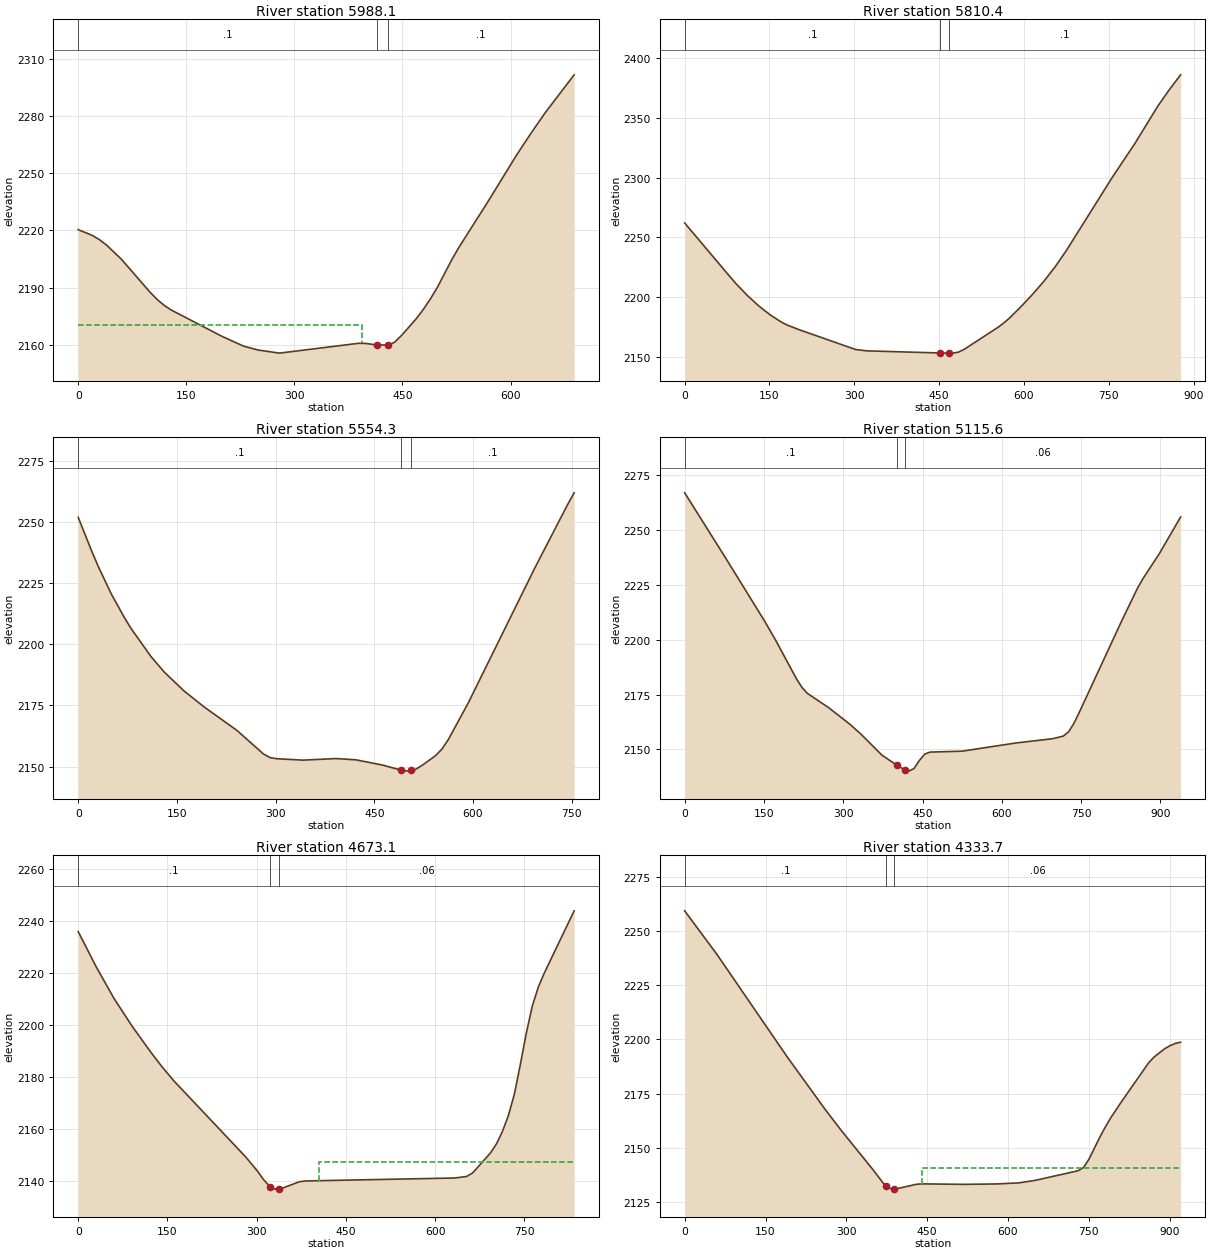
Type RM Length L Ch R = 1 ,5988.1  ,185.5,177.7,169.9
XS GIS Cut Line= 2
     2190639.769      309188.801     2190726.913       309871.43
#Sta/Elev= 30
       0 2220.42      20 2217.34    29.9 2215.05    39.9 2212.14    59.8 2204.97
    99.7 2187.63   109.7 2183.78   119.7 2180.61   129.7 2178.18   199.5 2164.51
   229.4 2159.38   249.3 2157.36   279.3 2155.71     389 2160.86   398.9  2160.8
     415 2159.94     430 2159.98   438.8 2161.35   448.8 2165.02   468.8  2173.6
   478.7  2178.5   488.7  2184.1   498.7 2190.39   518.6  2204.8   528.6 2211.31
   568.5 2235.04   608.4 2259.55   628.3 2270.94   648.3 2281.83   688.2 2301.55
#Mann= 3 , 0 , 0
       0      .1       0     415    .045       0     430      .1       0
#XS Ineff= 2 , 0
          393.64 2170.71
Permanent Ineff=
       F       F
Bank Sta=415,430
XS Rating Curve= 0 ,0
Exp/Cntr=0.3,0.1

Type RM Length L Ch R = 1 ,5810.4  ,252.7,256.1,259.5
XS GIS Cut Line= 2
     2190316.297      309241.805     2190711.012      310025.162
#Sta/Elev= 30
       0  2262.1    80.7 2216.83    90.7 2211.38   110.9 2201.42   131.1 2192.69
   151.2 2185.23   171.4  2179.1   181.5 2176.66   201.6 2172.98   302.5 2156.21
   322.6 2155.11   452.1 2153.34   463.8 2153.22   467.1 2153.22   473.9 2153.22
     484 2154.01     494 2156.26   554.5  2174.9   564.6  2178.5   574.7 2182.61
   594.9 2192.12     615 2202.26   635.2 2213.21   655.4 2225.52   675.5 2239.33
   756.2 2300.19   796.5 2328.74   836.8 2359.82     857 2373.48   877.2 2386.05
#Mann= 3 , 0 , 0
       0      .1       0   452.1    .045       0   467.1      .1       0
Bank Sta=452.1,467.1
XS Rating Curve= 0 ,0
Exp/Cntr=0.3,0.1

Type RM Length L Ch R = 1 ,5554.3  ,431.5,438.7,445.8
XS GIS Cut Line= 2
     2190149.334      309307.473     2190383.127      310024.032
#Sta/Elev= 30
       0 2251.86    20.1 2238.32    30.2 2231.94    50.2 2220.58    70.4 2210.76
    80.4  2206.4   110.6 2194.95   130.6 2188.65   160.8  2180.9     191 2174.42
   241.2 2164.77   281.4 2155.14   291.4 2153.66   301.5 2153.18   341.7  2152.6
   391.9 2153.25   422.1 2152.73   462.3  2150.6   491.3 2148.47   502.5 2148.11
   506.3 2148.38   512.5 2148.81   522.6 2150.46   542.7 2154.36   552.7 2157.09
   562.8 2161.16   592.9 2176.05   693.4 2230.88   743.7 2257.04   753.7 2261.88
#Mann= 3 , 0 , 0
       0      .1       0   491.3    .045       0   506.3      .1       0
Bank Sta=491.3,506.3
XS Rating Curve= 0 ,0
Exp/Cntr=0.3,0.1

Type RM Length L Ch R = 1 ,5115.6  ,450.6,442.5,434.3
XS GIS Cut Line= 2
     2189873.034      309401.597     2189869.997      310339.804
#Sta/Elev= 30
       0 2267.05    80.7 2236.08   151.3 2208.51   171.5 2200.11   211.8 2182.08
   221.9  2178.3     232 2175.62   272.4 2169.07   312.7 2161.47   332.9 2157.13
   373.3  2147.4   401.9 2142.75   416.9 2140.66   423.7 2140.13   433.8  2141.3
   443.9 2144.94     454 2147.87   464.1 2148.81   524.6 2149.22   625.5 2152.93
   696.1 2154.93   716.3  2156.1   726.4  2158.1   736.4 2161.89   746.5 2166.93
   827.2 2208.88   857.5 2223.97   867.6 2228.14   897.9 2239.29   938.2 2256.04
#Mann= 3 , 0 , 0
       0      .1       0   401.9    .045       0   416.9     .06       0
Bank Sta=401.9,416.9
XS Rating Curve= 0 ,0
Exp/Cntr=0.3,0.1

Type RM Length L Ch R = 1 ,4673.1  ,341,339.4,337.9
XS GIS Cut Line= 2
     2189344.723      309641.463     2189630.132       310424.82
#Sta/Elev= 30
       0 2236.04    30.1 2222.52    60.3 2210.23    90.4 2199.64   120.5 2190.02
   140.6 2183.99   160.7 2178.51   281.3 2149.22   301.4 2143.68   311.4 2140.45
   322.5 2137.71   331.5 2136.74   337.5 2136.88   341.5 2136.98   371.7 2139.57
   381.7 2139.89   632.8 2141.03   652.9 2141.61     663 2142.98   693.1  2150.7
   703.2 2154.22   713.2 2159.01   723.2 2165.14   733.3 2173.43   743.3 2184.86
   753.4 2197.02   763.4 2207.36   773.5 2214.68   783.5 2220.04   833.7 2244.05
#Mann= 3 , 0 , 0
       0      .1       0   322.5    .045       0   337.5     .06       0
#XS Ineff= 2 , 0
                          404.37         2147.27
Permanent Ineff=
       F       F
Bank Sta=322.5,337.5
XS Rating Curve= 0 ,0
Exp/Cntr=0.3,0.1

Type RM Length L Ch R = 1 ,4333.7  ,483.8,471.3,458.8
XS GIS Cut Line= 2
     2188983.407      309717.369     2189356.868      310558.416
#Sta/Elev= 30
       0  2259.4      60 2239.23     190 2192.01   260.1 2167.85   290.1 2158.09
   350.1  2139.6   370.1 2133.06   373.4 2132.46   380.1 2131.25   388.4 2130.91
   390.1 2130.84   430.1 2133.08   440.1 2133.27   520.1 2133.04   580.2 2133.24
   620.2 2133.74   650.2 2134.87   730.2 2139.34   740.2 2140.87   750.2 2144.69
   770.2  2154.8   780.2  2159.4   790.2 2163.64   810.2 2171.11   860.2 2188.96
   870.2  2191.7   890.2 2195.63   900.2 2197.06   910.2 2198.13   920.2 2198.73
#Mann= 3 , 0 , 0
       0      .1       0   373.4    .045       0   388.4     .06       0
#XS Ineff= 2 , 0
                          439.79         2140.64
Permanent Ineff=
       F       F
Bank Sta=373.4,388.4
XS Rating Curve= 0 ,0
Exp/Cntr=0.3,0.1

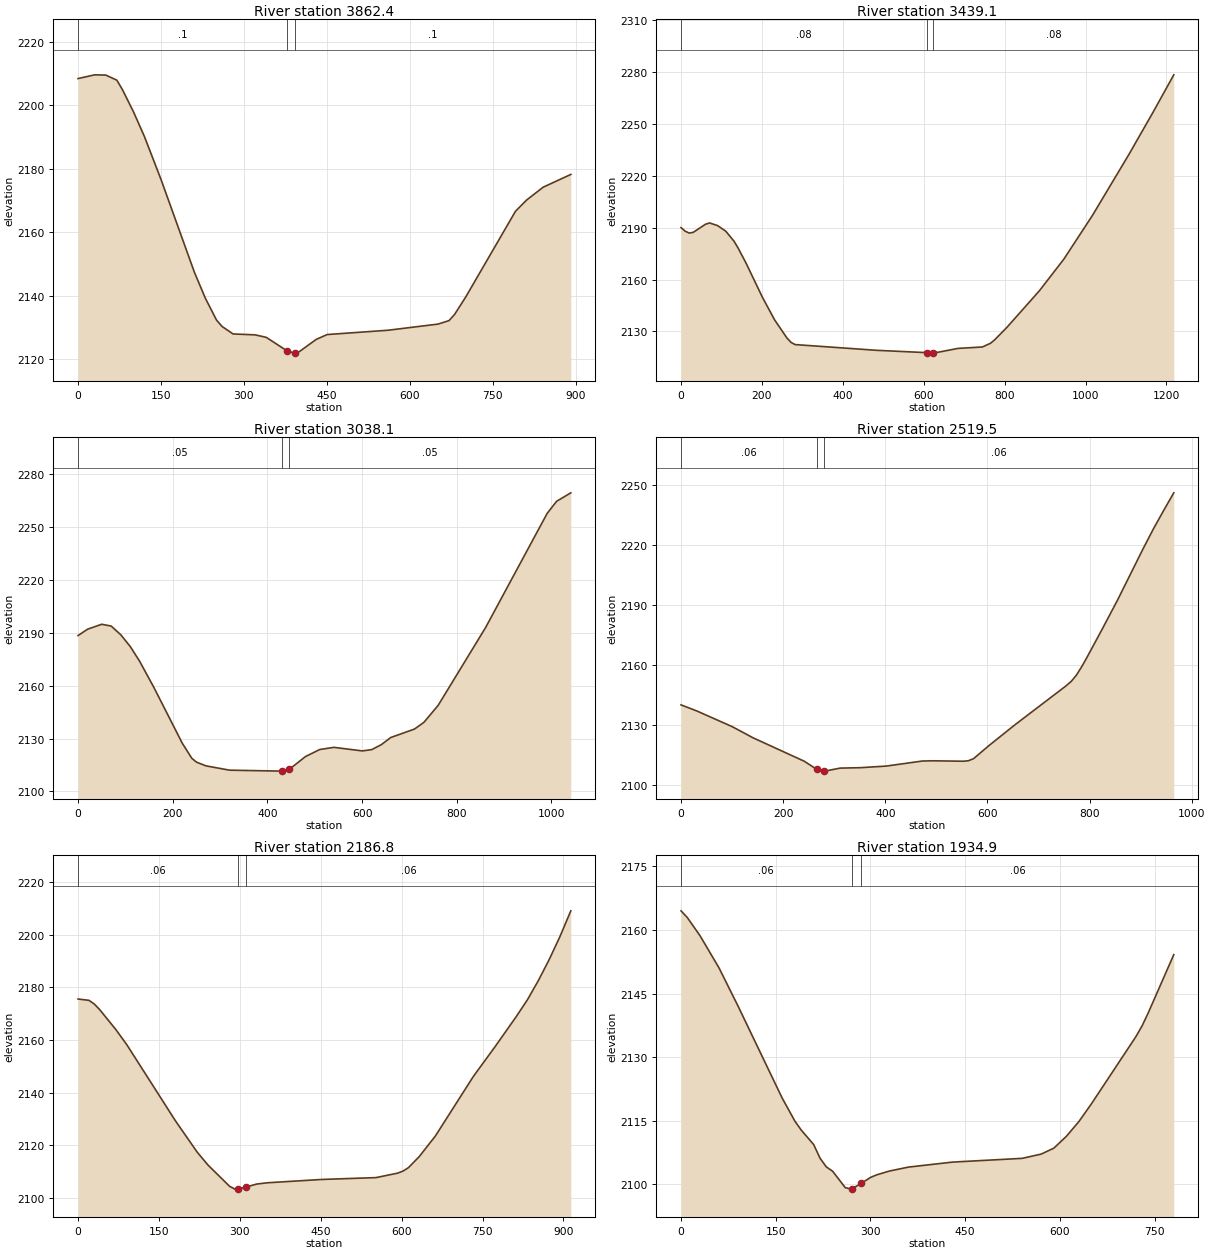
Type RM Length L Ch R = 1 ,3862.4  ,423.3,423.2,422.9
XS GIS Cut Line= 2
     2188461.169      310109.048     2189189.873      310622.177
#Sta/Elev= 30
       0 2208.34      30 2209.52    50.1 2209.44    70.1 2207.84    80.1 2204.91
   100.1 2197.93   120.2 2190.02   150.2 2176.49   210.3  2147.4   230.3 2139.14
   250.4 2132.29   260.4 2130.27   280.4 2127.91   320.4 2127.62   340.5 2126.83
   377.3 2122.66   390.5 2121.87   392.3 2121.96   400.6 2122.39   430.6 2126.18
   450.6 2127.72   560.8 2129.08   650.9 2131.01   670.9  2132.1     681 2134.07
     701  2139.5   791.1 2166.54   811.1 2170.06   841.2 2174.13   891.2 2178.15
#Mann= 3 , 0 , 0
       0      .1       0   377.3    .045       0   392.3      .1       0
Bank Sta=377.3,392.3
XS Rating Curve= 0 ,0
Exp/Cntr=0.3,0.1

Type RM Length L Ch R = 1 ,3439.1  ,388.7,401,413.2
XS GIS Cut Line= 2
     2188033.055       310318.55     2189028.951      311019.928
#Sta/Elev= 30
       0 2190.01    10.1 2187.97    20.1 2186.86    30.2 2187.26    60.4 2191.94
    70.5 2192.71    90.6 2191.14   110.7 2187.93   130.9 2182.18   140.9  2178.3
   161.1 2169.34   201.3 2149.73   231.5 2136.65   261.7  2126.3   271.8 2123.74
   281.9 2122.44   483.2 2119.13   609.1 2117.76   624.1  2117.5   684.6 2120.22
     745 2121.05   765.1 2123.21   775.2 2125.16   805.4 2132.33   885.9 2153.52
   946.3 2171.78  1016.8 2196.95  1107.4 2232.35  1167.8 2257.03  1218.1 2278.26
#Mann= 3 , 0 , 0
       0     .08       0   609.1    .045       0   624.1     .08       0
Bank Sta=609.1,624.1
XS Rating Curve= 0 ,0
Exp/Cntr=0.3,0.1

Type RM Length L Ch R = 1 ,3038.1  ,526.2,518.6,510.6
XS GIS Cut Line= 2
     2187981.439      310376.239     2188412.589      311323.555
#Sta/Elev= 30
       0 2188.42      20 2192.01      50 2194.84      70 2193.81    90.1 2188.92
   110.1 2182.26   130.1 2173.84   160.1 2159.04   220.2 2127.33   240.2 2118.82
   250.2  2116.6   270.2 2114.49   320.2 2112.05   430.3 2111.51   430.9 2111.52
   445.9 2112.46   480.4 2119.78   510.4 2123.76   540.4    2125   600.5 2122.98
   620.5 2123.72   640.5 2126.52   660.5 2130.58   710.6 2135.38   730.6 2139.21
   760.6 2148.82   860.7 2192.92   990.8 2257.72  1010.8  2264.6  1040.8 2269.41
#Mann= 3 , 0 , 0
       0     .05       0   430.9    .045       0   445.9     .05       0
Bank Sta=430.9,445.9
XS Rating Curve= 0 ,0
Exp/Cntr=0.3,0.1

Type RM Length L Ch R = 1 ,2519.5  ,331.7,332.7,333.6
XS GIS Cut Line= 2
     2187544.216      310667.721     2188193.977      311381.244
#Sta/Elev= 30
       0    2140    30.2 2137.03   100.5 2129.07   140.7 2123.56   241.3  2111.8
   265.4  2107.8   271.4 2107.01   280.4 2106.86   281.5 2106.84   311.6 2108.35
   351.8 2108.57   402.1 2109.37   472.5 2111.89   492.6 2112.01   552.9 2111.79
   562.9 2112.04     573  2113.1   603.2 2119.66   653.4 2129.92   753.9  2149.5
     764 2151.71     774 2154.77   784.1 2158.86   794.2  2163.4   824.3 2177.65
   854.5 2192.27   904.7 2218.02   924.8 2227.93   944.9 2237.17     965 2246.12
#Mann= 3 , 0 , 0
       0     .06       0   265.4    .045       0   280.4     .06       0
Bank Sta=265.4,280.4
XS Rating Curve= 0 ,0
Exp/Cntr=0.3,0.1

Type RM Length L Ch R = 1 ,2186.8  ,242.4,251.9,261.2
XS GIS Cut Line= 2
     2187267.916      310834.716     2187856.952      311533.058
#Sta/Elev= 30
       0  2175.6    20.1  2175.1    30.1  2173.7    40.2 2171.54    70.3 2163.92
    90.4 2158.21   180.7  2129.2   220.9 2117.33     241  2112.4   281.1  2104.3
   291.1 2103.25   297.3 2103.33   312.3 2104.12   331.3 2105.18   351.4 2105.67
   451.8 2106.93   552.2 2107.63   592.3 2109.32   602.4 2110.11   612.4 2111.39
   632.5 2115.61   662.6  2123.5   732.9 2146.13     773 2157.41   813.2 2169.13
   833.3 2175.36   853.4 2182.61   873.4 2190.56   893.5 2199.38   913.6 2209.16
#Mann= 3 , 0 , 0
       0     .06       0   297.3    .045       0   312.3     .06       0
Bank Sta=297.3,312.3
XS Rating Curve= 0 ,0
Exp/Cntr=0.3,0.1

Type RM Length L Ch R = 1 ,1934.9  ,349.2,348.3,346.9
XS GIS Cut Line= 2
     2187185.936      310937.949     2187401.511      311687.907
#Sta/Elev= 30
       0 2164.54      10 2162.95      30 2158.69      60 2151.12      90 2142.16
   160.1 2120.39   180.1 2114.98   190.1 2112.86   210.1 2109.39   220.1 2106.19
   230.1 2104.12   240.1  2103.1   260.1 2099.23   270.1 2098.88   285.1 2100.22
   300.1 2101.64   310.1 2102.26   330.1 2103.15   360.2 2104.08   430.2 2105.26
   540.2 2106.14   570.2 2107.14   590.2 2108.53   610.3 2111.35   630.3 2114.87
   650.3  2119.1   720.3 2134.85   730.3 2137.45   740.3 2140.61   780.3  2154.2
#Mann= 3 , 0 , 0
       0     .06       0   270.1    .045       0   285.1     .06       0
Bank Sta=270.1,285.1
XS Rating Curve= 0 ,0
Exp/Cntr=0.3,0.1

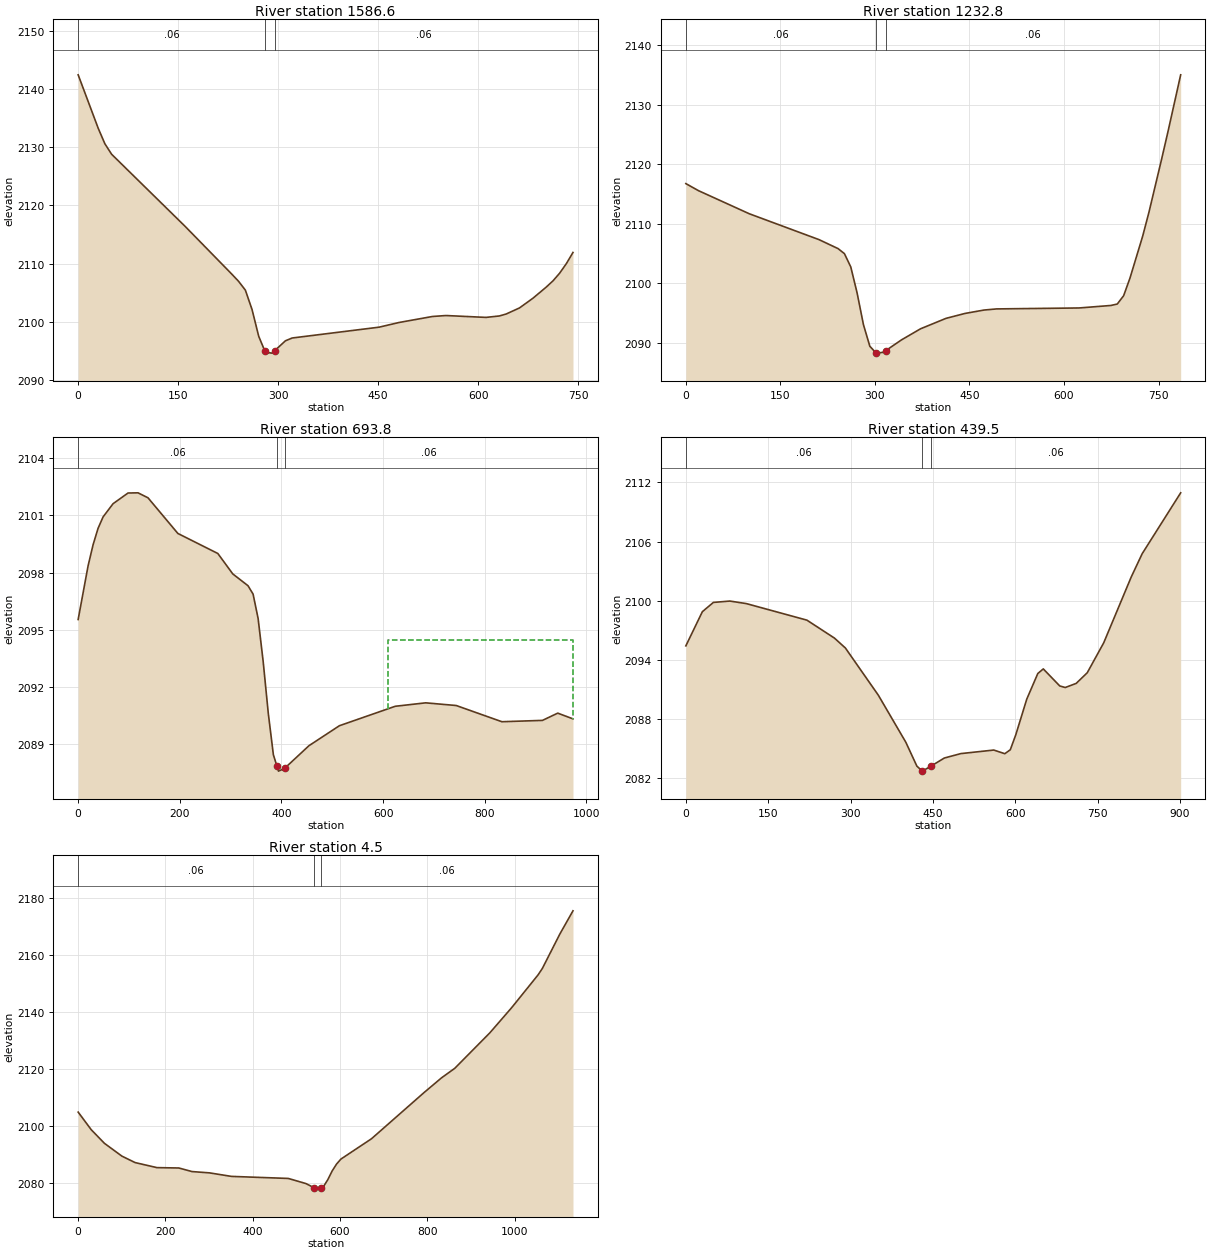
Type RM Length L Ch R = 1 ,1586.6  ,350.8,353.8,356.7
XS GIS Cut Line= 2
     2186836.766      311019.928     2187079.667      311721.306
#Sta/Elev= 30
       0 2142.43    30.1 2133.24    40.1 2130.58    50.2 2128.78   160.5 2116.38
   230.7 2108.15   240.7 2106.93   250.8 2105.43   260.8  2102.1   270.8  2097.5
   279.8 2095.02   280.8 2094.74   290.9  2094.6   294.8 2095.02   310.9 2096.72
     321  2097.2   451.4 2099.06   481.5 2099.87   531.6  2100.9   551.7 2101.06
   611.8 2100.74   631.9 2100.99   641.9 2101.32     662 2102.37   682.1 2104.03
   702.1 2105.95   712.2 2107.02   722.2 2108.34   732.2 2109.97   742.2  2111.9
#Mann= 3 , 0 , 0
       0     .06       0   279.8    .045       0   294.8     .06       0
Bank Sta=279.8,294.8
XS Rating Curve= 0 ,0
Exp/Cntr=0.3,0.1

Type RM Length L Ch R = 1 ,1232.8  ,543.4,539,534.5
XS GIS Cut Line= 2
     2186545.284      311141.379     2186721.387      311906.519
#Sta/Elev= 30
       0 2116.71    20.1 2115.52   100.7 2111.64   211.4 2107.29   241.6 2105.78
   251.6 2104.94   261.7  2102.7   271.8  2098.3   281.8    2093   291.9 2089.38
     302 2088.22   302.3 2088.22     312 2088.34   317.3 2088.65   342.2 2090.45
   372.4 2092.31   412.7 2094.06   442.9 2094.89   473.1 2095.46   493.2 2095.65
   624.1 2095.81   674.4 2096.23   684.5 2096.47   694.6 2097.87   704.6 2100.81
   724.8 2107.87   734.8 2111.91     755 2120.88     765 2125.46   785.1 2134.99
#Mann= 3 , 0 , 0
       0     .06       0   302.3    .045       0   317.3     .06       0
Bank Sta=302.3,317.3
XS Rating Curve= 0 ,0
Exp/Cntr=0.3,0.1

Type RM Length L Ch R = 1 ,693.8   ,227.9,254.3,280.9
XS GIS Cut Line= 3
     2186109.074      311223.857     2186083.771      311526.985
      2186344.89      312143.347
#Sta/Elev= 30
       0 2095.54    19.6 2098.36    29.4 2099.46    39.2 2100.32    49.1 2100.92
    68.7 2101.61    98.1 2102.17   117.8 2102.18   137.4 2101.92   196.2 2100.05
   274.8    2099   304.2 2097.93   334.2 2097.31   344.2 2096.87   354.1 2095.59
   364.1 2093.32   374.1 2090.62   384.1 2088.45     391 2087.86   394.1 2087.59
     406 2087.73     454 2088.92     514 2089.97   623.9 2090.99   683.8 2091.17
   743.8 2091.03   833.7 2090.18   913.6 2090.25   943.6 2090.63   973.6 2090.33
#Mann= 3 , 0 , 0
       0     .06       0     391    .045       0     406     .06       0
#XS Ineff= 2 , 0
                          609.89         2094.49
Permanent Ineff=
       F       F
Bank Sta=391,406
XS Rating Curve= 0 ,0
Exp/Cntr=0.3,0.1

Type RM Length L Ch R = 1 ,439.5   ,427.4,434.9,441.7
XS GIS Cut Line= 3
      2186069.77      311238.006     2185995.719      311508.767
     2185570.642      311961.171
#Sta/Elev= 30
       0 2095.41    30.1 2098.88    50.1 2099.82    80.2 2099.96   110.3  2099.7
   220.6 2098.02   270.7  2096.2   290.7 2095.19   350.8 2090.39   400.8 2085.62
   420.9  2083.2   430.8 2082.69   445.8 2083.17   470.9 2084.02     501 2084.47
     561 2084.83   581.1 2084.46   591.1 2084.86   601.1 2086.38   621.1    2090
   641.2  2092.6   651.2 2093.07   681.2 2091.34   691.2 2091.18   711.2  2091.6
   731.3 2092.68   761.3 2095.72   811.4  2102.4   831.4 2104.77   901.5 2110.95
#Mann= 3 , 0 , 0
       0     .06       0   430.8    .045       0   445.8     .06       0
Bank Sta=430.8,445.8
XS Rating Curve= 0 ,0
Exp/Cntr=0.3,0.1

Type RM Length L Ch R = 1 ,4.5     ,3.3,4.5,5.8
XS GIS Cut Line= 2
     2186001.811      311175.252     2185019.567      311742.024
#Sta/Elev= 30
       0 2104.91    30.1 2098.73    60.2 2093.98   100.4 2089.48   130.5 2087.24
   180.6 2085.47   230.8 2085.34   260.9 2084.09   301.1 2083.63   351.2  2082.4
   481.7 2081.68   521.9 2079.89   540.4 2078.47     552 2077.94   555.4 2078.23
     562 2078.79     572 2081.21   582.1  2084.3   592.1  2086.7   602.1 2088.45
   672.4  2095.6   792.8 2111.77     833 2116.94   863.1 2120.25   943.4 2132.66
   993.5 2141.49  1053.8 2152.93  1063.8 2155.22  1103.9 2167.27    1134  2175.4
#Mann= 3 , 0 , 0
       0     .06       0   540.4    .045       0   555.4     .06       0
Bank Sta=540.4,555.4
XS Rating Curve= 0 ,0
Exp/Cntr=0.3,0.1
Stream Node=SlshLckRun      ,Main            , 0 , 0 ,Upstream end
Stream Node=SlshLckRun      ,Main            , 0 , 1 ,Downstream end

Chan Stop Cuts=-1
Use User Specified Reach Order=0
Composite Channel Slope=5